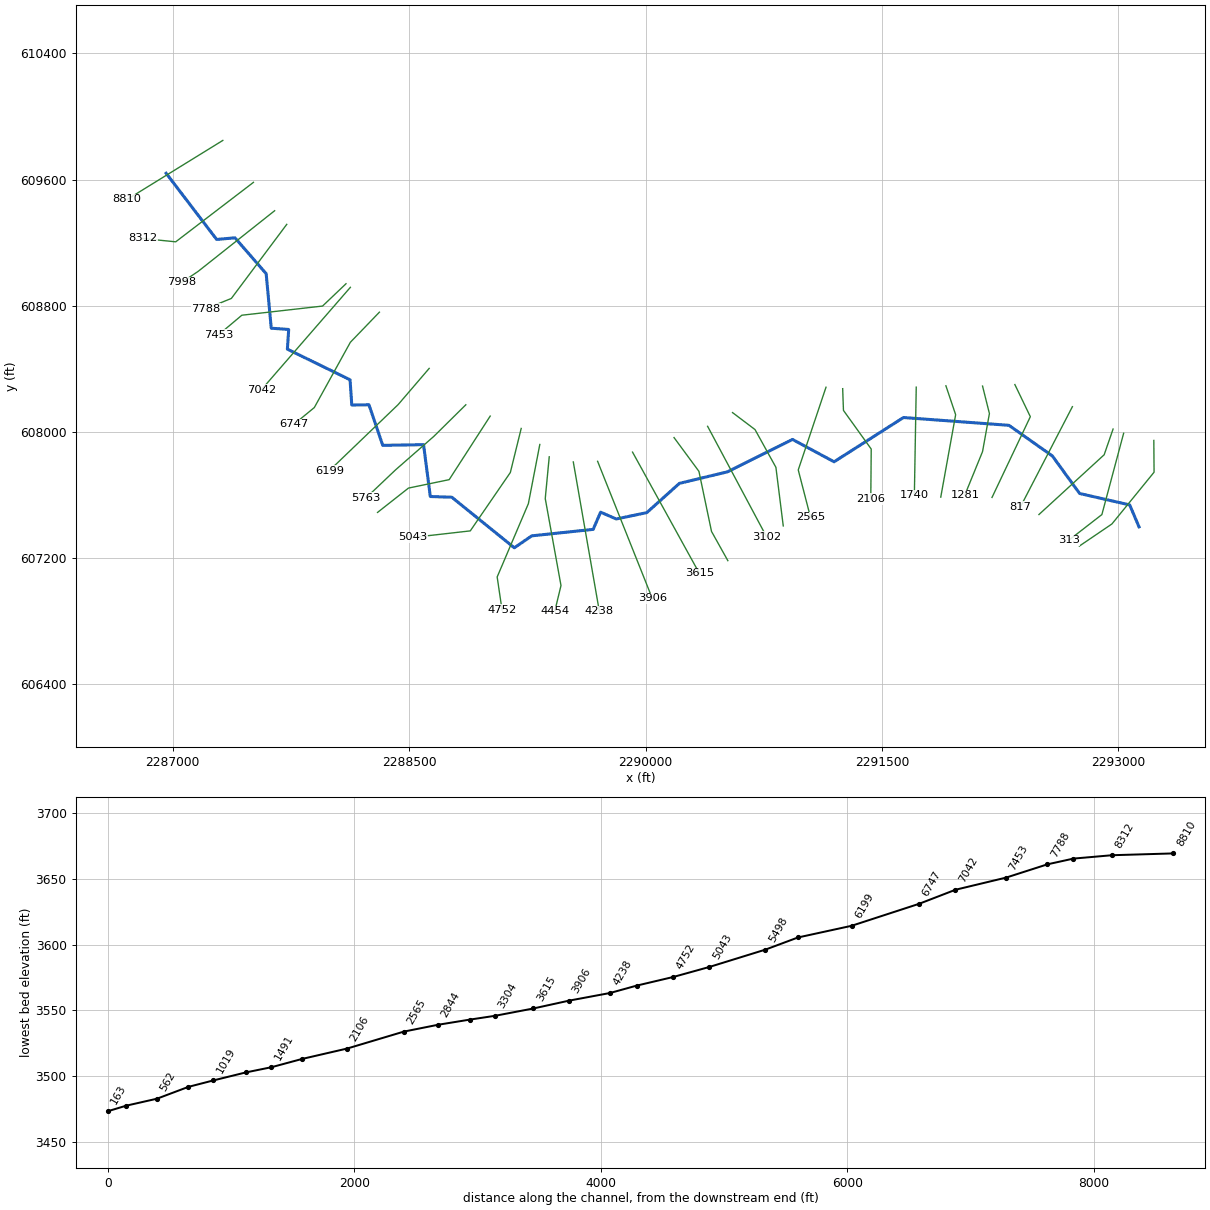
--- WHITMEADRN.prj (project) ---

Proj Title=WHITMEADRN
Current Plan=p01
Default Exp/Contr=0,0
English Units
Geom File=g01
Flow File=f01
Plan File=p01
BEGIN DESCRIPTION:
----------MODEL BY WOOD PLC 2022----------
AFH study
Randolph County, WV
HEC-RAS Version: RAS 6.2
Vertical Datum: NAVD88
Projection: NAD 1983 StatePlane West Virginia S FIPS 4702 (US Feet)
Terrain: 1-meter LIDAR (FEMA Region III 3DEP collected 2016-2018)
Land Use: 2019 NLCD
Hydrologic Method:
WV SIR2010-5033 regression equations
Additional Model Notes:
None
END DESCRIPTION:
DSS Export Rating Curves= 0
DSS Export Rating Curve Sorted= 0
DSS Export Volume Flow Curves= 0
DXF OffsetX= 0
DXF OffsetY= 0
DXF ScaleX= 0
DXF ScaleY= 0

--- WHITMEADRN.p01 (plan) ---

Plan Title=Floodplain
Program Version=6.20
Short Identifier=Floodplain
Geom File=g01
Flow File=f01
Subcritical Flow
K Sum by GR= 0
Std Step Tol= 0.01
Critical Tol= 0.01
Num of Std Step Trials= 20
Max Error Tol= 0.3
Flow Tol Ratio= 0.001
Split Flow NTrial= 30
Split Flow Tol= 0.02
Split Flow Ratio= 0.02
Log Output Level= 0
Friction Slope Method= 1
Unsteady Friction Slope Method= 2
Unsteady Bridges Friction Slope Method= 1
Parabolic Critical Depth
Global Vel Dist= 0 , 0 , 0
Global Log Level= 0
CheckData=True
Encroach Param=-1 ,0,0, 0
Mapping Interval=1HOUR
Computation Time Step Use Courant=        0
Computation Time Step Use Time Series=    0
Computation Time Step Count To Double=0
Computation Time Step Max Doubling=0
Computation Time Step Max Halving=0
Computation Time Step Residence Courant=0
Run HTab= 0
Run UNet= 0
Run Sediment= 0
Run PostProcess= 0
Run WQNet= 0
Run RASMapper= 0
UNET Theta= 0
UNET Theta Warmup= 0
UNET ZTol= 0
UNET ZSATol= 0
UNET MxIter= 0
UNET Max Iter WO Improvement= 0
UNET MaxInSteps= 0
UNET DtIC= 0
UNET DtMin= 0
UNET MaxCRTS= 0
UNET WFStab= 0
UNET SFStab= 0
UNET WFX= 1
UNET SFX= 1
UNET Gravity=32.174
UNET 1D Methodology=Finite Difference
UNET DSS MLevel= 1
UNET Pardiso=0
UNET DZMax Abort= 0
UNET Use Existing IB Tables= 0
UNET Froude Reduction=False
UNET Froude Limit= 0
UNET Froude Power= 0
UNET D1 Cores= 0
UNET WindReference=Eulerian
UNET WindDragFormulation=Hsu (1988)
UNET D2 Coriolis=0
UNET D2 Cores= 0
UNET D2 Theta= 1
UNET D2 Theta Warmup= 1
UNET D2 Z Tol= 0.01
UNET D2 Volume Tol= 0.01
UNET D2 Max Iterations= 20
UNET D2 Equation= 0
UNET D2 RampUpFraction=0.1
UNET D2 TimeSlices= 1
UNET D2 Turbulence Formulation=Non-Conservative (original)
UNET D2 Eddy Viscosity=0.3
UNET D2 Transverse Eddy Viscosity=0.1
UNET D2 Smagorinsky Mixing=0
UNET D2 BCVolumeCheck=0
UNET D2 Cores=0
UNET D2 SolverType=PARDISO (Direct)
UNET D2 Minimum Iterations= 2147483647
UNET D2 Maximum Iterations= 2147483647
UNET D2 Restart Number= 10
UNET D2 Relaxation Coeff=1.3
UNET D2 SOR Precondition Iterations= 10
UNET D2 ILUT Maximum Fill= 8
UNET D2 ILUT Tolerance=1E-08
UNET D1D2 MaxIter= 0
UNET D1D2 ZTol=0.01
UNET D1D2 QTol=0.1
UNET D1D2 MinQTol=1
Write IC File= 0
Write IC File at Fixed DateTime=0
Write IC File at Sim End=0
Echo Input=False
Echo Parameters=False
Echo Output=False
Write Detailed= 0
HDF Write Warmup=0
HDF Write Time Slices=0
HDF Flush=0
HDF Compression= 1
HDF Chunk Size= 1
HDF Spatial Parts= 1
HDF Use Max Rows=0
HDF Fixed Rows= 1
Calibration Method= 0
Calibration Iterations= 20
Calibration Max Change=0.05
Calibration Tolerance=0.2
Calibration Maximum=1.5
Calibration Minimum=0.5
Calibration Optimization Method= 1
WQ AD Non Conservative
WQ ULTIMATE=-1
WQ Max Comp Step=1HOUR
WQ Output Interval=15MIN
WQ Output Selected Increments= 0
WQ Output face flow=0
WQ Output face velocity=0
WQ Output face area=0
WQ Output face dispersion=0
WQ Output cell volume=0
WQ Output cell surface area=0
WQ Output cell continuity=0
WQ Output cumulative cell continuity=0
WQ Output face conc=0
WQ Output face dconc_dx=0
WQ Output face courant=0
WQ Output face peclet=0
WQ Output face adv mass=0
WQ Output face disp mass=0
WQ Output cell mass=0
WQ Output cell source sink temp=0
WQ Output nsm pathways=0
WQ Output nsm derived pathways=0
WQ Create Restart=0
WQ Fixed Restart=0
WQ System Summary=0
WQ Write To DSS=0
Sorting and Armoring Iterations= 10
XS Update Threshold= 0.02
Bed Roughness Predictor= 0
Hydraulics Update Threshold= 0.02
Energy Slope Method= 1
Volume Change Method= 1
Sediment Retention Method= 0
Sediment TS Multiplier= 1
Warm Up Method= 0
XS Weighting Method= 0
Number of US Weighted Cross Sections= 1
Number of DS Weighted Cross Sections= 1
Upstream XS Weight=0
Main XS Weight=1
Downstream XS Weight=0
Number of DS XS's Weighted with US Boundary= 1
Upstream Boundary Weight= 1
Weight of XSs Associated with US Boundary= 0
Number of US XS's Weighted with DS Boundary= 1
Downstream Boundary Weight= 0.5
Weight of XSs Associated with DS Boundary= 0.5
Percentile Method= 0
Sediment Output Level= 3
Mass or Volume Output= 0
Output Increment Type= 1
Profile and TS Output Increment= 1
Transport Output Increment 1
XS Output Flag= 0
XS Output Increment= 10
Read HDF5 Sediment Hotstart= 0
Sediment Hotstart Type= 0
Write Gradation File= 0
Read Gradation Hotstart= 0
Write HDF5 File= 1
Write Binary Output= 1
Write DSS Sediment File= 0
DSS Sediment Output Type= 1
SV Curve= 0
Specific Gage Flag= 0
Subcell Erosion Methods= 0
Subcell Deposition Methods= 0
Advection Scheme= 1
Matrix Solver= 0
Implicit Weighting Factor= 1
Maximum Outer Loop Convergence Iterations= 5
Convergence Maximum Absolute= 0.001
Convergence RMSE= 0.0001
Grain Fractions Max Abs Error= 0.001
Max Subgrid Regions= 1
Max Subgrid Length Scale= 3.402823E+38
Initial Layer Thickness= 3.402823E+38
Min Layer Thickness= 3.402823E+38
Max Layer Thickness= 3.402823E+38
Number of Layers= 5

--- WHITMEADRN.f01 (steady flow) ---

Flow Title=Flow
Program Version=4.00
Number of Profiles=1
Profile Names=P100yr
River Rch & RM=WHITMEADRN,Main,8810
     339
River Rch & RM=WHITMEADRN,Main,7453
     379
River Rch & RM=WHITMEADRN,Main,5043
     530
River Rch & RM=WHITMEADRN,Main,2565
     609
River Rch & RM=WHITMEADRN,Main,2106
     679
Boundary for River Rch & Prof#=WHITMEADRN,Main      ,1
Up Type=0
Dn Type=3
Dn Slope=0.028897

--- WHITMEADRN.g01 (geometry) ---

Geom Title=Geometry
Program Version=6.20

River Reach=WHITMEADRN      ,Main
Reach XY= 30
     2286958.099      609639.769     2287278.671      609219.717
     2287395.034      609230.025     2287592.886      609002.504
     2287625.134       608656.54      2287735.79      608648.554
     2287727.456      608523.554     2288125.164      608329.327
     2288136.044      608169.257      2288245.13      608170.704
      2288332.63      607913.239     2288591.484      607917.579
     2288634.409      607588.593     2288770.868      607584.036
     2289167.343      607263.272     2289278.208      607339.061
     2289667.748      607380.076      2289714.84      607489.234
     2289814.016      607446.048     2290007.876       607486.32
     2290214.867      607671.978     2290519.082       607745.05
     2290932.569      607950.774     2291196.316      607808.925
     2291636.529       608089.77      2292305.74      608040.281
     2292581.242      607846.0422292754.18167782 607607.80167304
     2293071.985      607535.243     2293131.221      607396.092

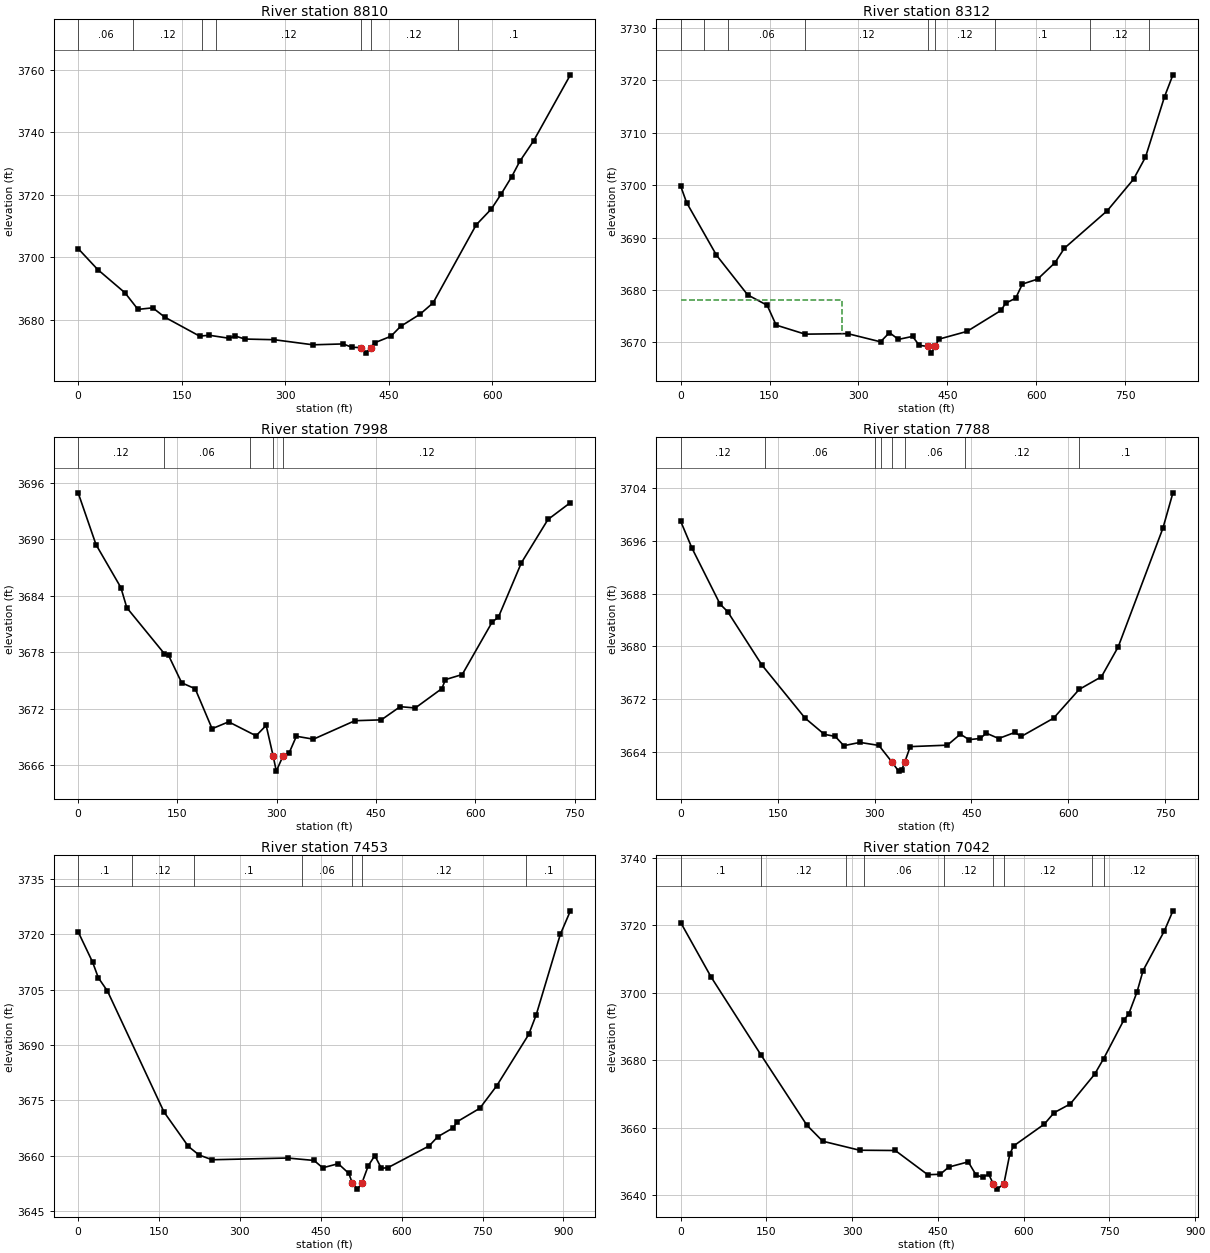
Type RM Length L Ch R = 1 ,8810    ,487.5,498.2,491.2
XS GIS Cut Line= 2
2287317.98079986609848.1137999162286710.74420035609473.403800217
#Sta/Elev= 30
       0 3702.76    28.4 3696.05    67.9 3688.62    86.7 3683.32   108.1 3683.82
   125.5 3680.85     176 3674.78   190.1 3675.05   218.5  3674.1   227.7  3674.8
   241.8 3673.84   284.1 3673.63   340.5    3672   384.2 3672.28   396.9 3671.19
   410.4 3671.13   416.9 3669.34  424.373671.127   429.8 3672.64   453.3 3674.73
   467.4 3677.89   495.6 3681.79   514.5 3685.41   576.9 3710.33   599.1 3715.46
   613.2 3720.22   628.4 3725.72     640  3730.6   660.2 3737.21   713.5  3758.3
#Mann= 7 ,-1,0
       0     .06       0      80     .12       0     180     .06       0
     200     .12       0   410.4    .045       0  424.37     .12       0
     550      .1       0
Bank Sta=410.4,424.37
XS Rating Curve= 0 ,0
Exp/Cntr=0.3,0.1

Type RM Length L Ch R = 1 ,8312    ,311.1,313.8,310
XS GIS Cut Line= 3
2287512.10356195609581.8822417522287018.86721158609204.614371678
  2286809.991142609225.789362433
#Sta/Elev= 30
       0 3699.83      10 3696.68    60.4 3686.65   113.1 3679.07     146 3677.09
   161.1 3673.31     210 3671.58   281.9 3671.68   337.3 3670.12   352.4 3671.87
   367.5 3670.58   391.4 3671.15   402.8 3669.44     417 3669.24   422.9 3667.96
  429.653669.268   435.7 3670.62   483.4 3672.11     541 3676.13   548.3 3677.48
   565.4 3678.43   576.8 3681.14   602.5 3682.08   631.7  3685.2   647.8 3687.99
   720.2 3695.15   764.4 3701.14   784.6 3705.36   816.7 3716.88   830.9 3721.06
#Mann= 9 ,-1,0
       0      .1       0      40     .12       0      80     .06       0
     210     .12       0     417    .045       0  429.65     .12       0
     530      .1       0  690.98     .12       0  790.98      .1       0
#XS Ineff= 2 , 0
          271.86 3678.08
Permanent Ineff=
       F       F
Bank Sta=417,429.65
XS Rating Curve= 0 ,0
Exp/Cntr=0.3,0.1

Type RM Length L Ch R = 1 ,7998    ,207,210.6,212.6
XS GIS Cut Line= 3
2287646.68942895609401.969179744 2287161.3659442609017.144711824
2287058.31444655 608947.93457084
#Sta/Elev= 30
       0 3694.92      27 3689.42    64.5 3684.87    73.5 3682.73     130 3677.87
   136.5 3677.68   156.4 3674.76   176.8 3674.13   202.3 3669.89   227.3 3670.62
   268.7 3669.14     284 3670.24  294.513666.995   299.3 3665.39   309.5 3667.01
   318.4 3667.28   329.6 3669.09   355.4 3668.78     418 3670.74   457.9 3670.83
   486.4 3672.23   509.2 3672.09   549.4 3674.15   554.7  3675.1   580.1 3675.64
   625.6 3681.24   634.6  3681.7   669.5  3687.5   709.6 3692.09   743.5 3693.88
#Mann= 5 ,-1,0
       0     .12       0     130     .06       0     260     .12       0
  294.51    .045       0   309.5     .12       0
Bank Sta=294.51,309.5
XS Rating Curve= 0 ,0
Exp/Cntr=0.3,0.1

Type RM Length L Ch R = 1 ,7788    ,342.4,335.1,326.1
XS GIS Cut Line= 3
2287723.42562716609315.3094257512287371.97178324608845.392118585
2287209.66073678608779.608221511
#Sta/Elev= 30
       0 3698.96    17.6 3694.86      61 3686.38    72.6 3685.26   125.6 3677.16
   192.4  3669.1   222.4 3666.62   239.2 3666.31   252.5  3664.9   277.4  3665.4
   306.8 3664.94   327.3 3662.38   337.3 3661.04   342.3 3661.28   346.93662.438
   355.3 3664.76   412.8 3664.98   432.9 3666.65   446.2 3665.82   463.9    3666
   472.9 3666.81   492.2 3665.99   517.1 3666.91   527.1  3666.3   577.1 3669.07
   616.8 3673.44   651.3 3675.37   677.2  3679.9   746.3 3697.88   761.9 3703.28
#Mann= 8 ,-1,0
       0     .12       0     130     .06       0     300     .12       0
     310     .06       0   327.3    .045       0   346.9     .06       0
     440     .12       0  616.81      .1       0
Bank Sta=327.3,346.9
XS Rating Curve= 0 ,0
Exp/Cntr(USF)=0,0
Exp/Cntr=0.3,0.1

Type RM Length L Ch R = 1 ,7453    ,399.9,411.2,414.7
XS GIS Cut Line= 4
2288099.57378583608938.6649051992287950.67342943608797.027980819
2287438.60147205608738.9205246632287291.51697366608615.442180331
#Sta/Elev= 30
       0  3720.7    26.8 3712.47    37.4 3708.24    54.4 3704.63   159.3 3671.84
   204.3 3662.55   224.1 3660.22   248.3 3658.92   388.4 3659.39   437.5 3658.73
   453.5 3656.74   482.4 3657.85   501.9 3655.23   508.3 3652.66     518 3650.96
   526.4 3652.66   538.1 3657.32   550.2 3660.03   562.3 3656.61   574.4 3656.77
   650.8 3662.66   666.9 3665.16   695.1 3667.53   703.2 3669.26   744.9 3672.87
   776.3 3678.97   835.6 3692.88   849.4 3698.15   894.2    3720   912.9 3726.38
#Mann= 7 ,-1,0
       0      .1       0     100     .12       0  215.51      .1       0
  415.51     .06       0   508.3    .045       0   526.4     .12       0
  830.86      .1       0
Bank Sta=508.3,526.4
XS Rating Curve= 0 ,0
Exp/Cntr(USF)=0,0
Exp/Cntr=0.3,0.1

Type RM Length L Ch R = 1 ,7042    ,292.1,294.9,296.8
XS GIS Cut Line= 2
2288127.06953375608915.8216716712287562.33769424608265.744505926
#Sta/Elev= 30
       0 3720.87    53.2 3704.69     140 3681.68   220.7 3660.71   248.4 3655.94
     313 3653.26   375.4 3653.18   432.1    3646   453.9 3646.11   468.9 3648.25
     503 3649.81   516.8 3645.89   528.5 3645.22   538.7 3646.16  546.62 3643.37
     554 3641.71  565.49 3643.37   575.7 3652.09   582.3 3654.52   636.2 3661.02
   653.2  3664.4   681.6 3667.01   724.1 3675.81     740 3680.48   775.2 3691.91
   783.7 3693.66   798.3 3700.26   808.9 3706.61     846 3718.34   861.1 3724.34
#Mann= 9 ,-1,0
       0      .1       0     140     .12       0     290      .1       0
     320     .06       0     460     .12       0  546.62    .045       0
  565.49     .12       0     720      .1       0     740     .12       0
Bank Sta=546.62,565.49
XS Rating Curve= 0 ,0
Exp/Cntr(USF)=0,0
Exp/Cntr=0.3,0.1

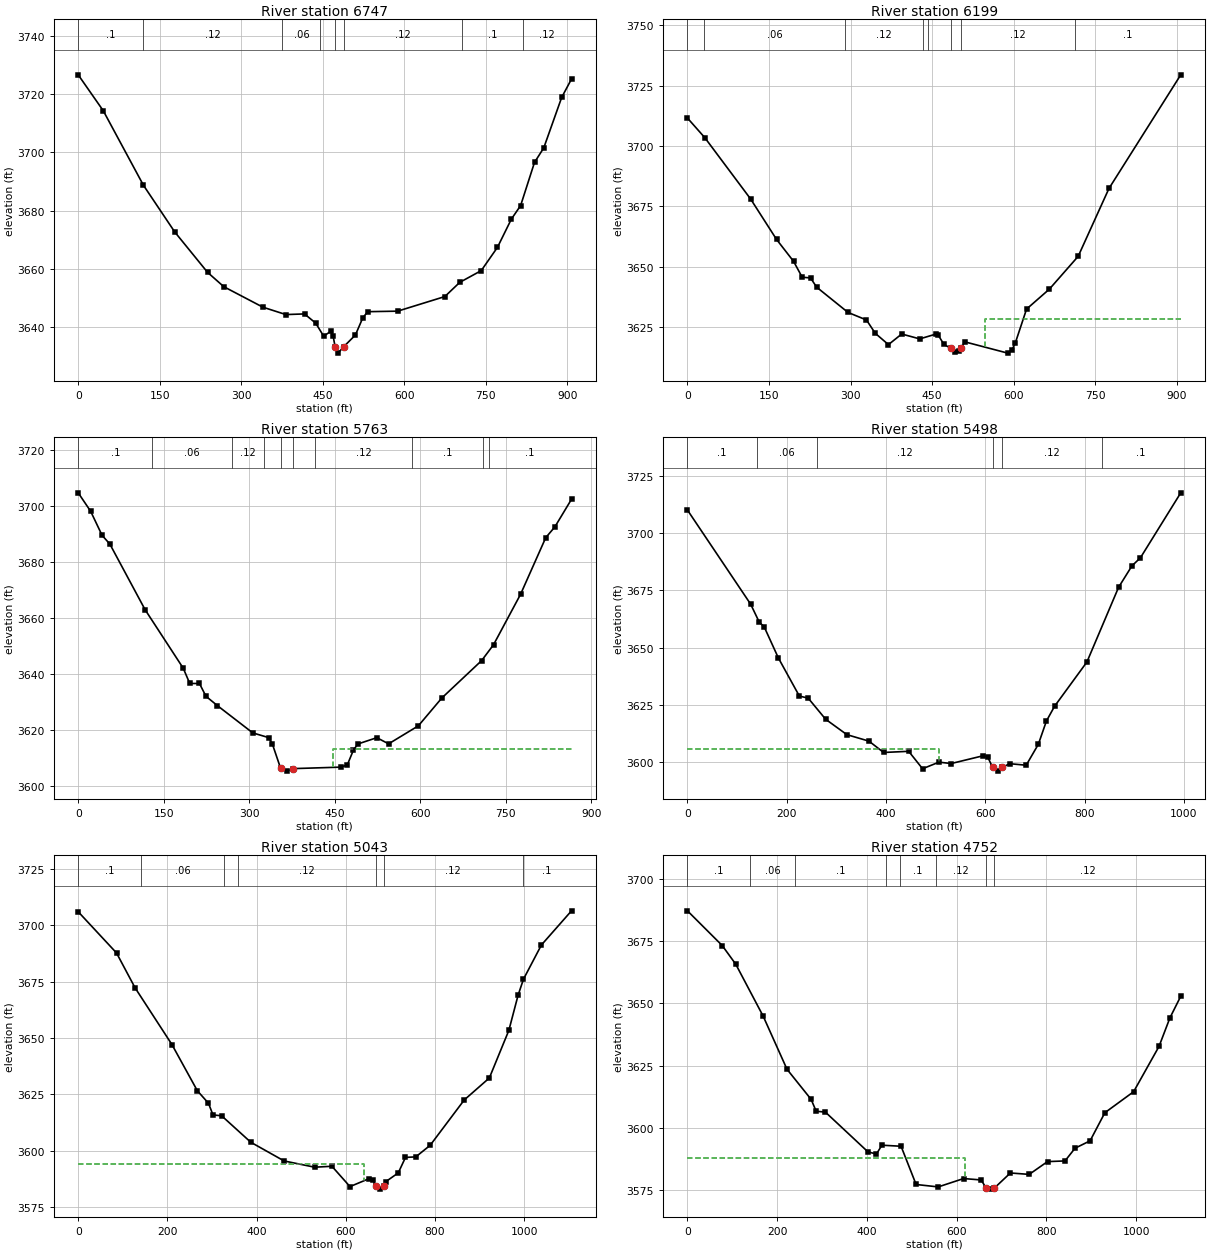
Type RM Length L Ch R = 1 ,6747    ,546.9,548.1,542.4
XS GIS Cut Line= 4
 2288311.5001963608758.3369818982288127.06953375608567.176934735
2287898.38325382608153.0491633082287767.85061022608045.676444088
#Sta/Elev= 30
       0 3726.59    46.1 3714.26     120 3688.68   177.6 3672.65     238 3658.78
   267.9 3653.85   339.9 3646.81   382.1 3644.28   416.4  3644.5     437 3641.34
   451.7 3636.85   464.4  3638.5     469 3636.96  472.683633.267   478.1 3631.04
  488.423633.223   510.1 3637.27   523.8 3643.23   532.9 3645.27   587.8 3645.45
   674.6 3650.46   702.1 3655.34   741.6 3659.37   771.4 3667.35     797 3677.04
   814.1 3681.72   839.6 3696.52   856.7 3701.53   889.6 3718.83   907.7 3725.15
#Mann= 8 ,-1,0
       0      .1       0     120     .12       0  375.63     .06       0
  445.63     .12       0  472.68    .045       0  488.42     .12       0
  705.63      .1       0   818.7     .12       0
Bank Sta=472.68,488.42
XS Rating Curve= 0 ,0
Exp/Cntr=0.3,0.1

Type RM Length L Ch R = 1 ,6199    ,434.2,435.5,433.8
BEGIN DESCRIPTION:
Disconnected without IFA
END DESCRIPTION:
XS GIS Cut Line= 3
2288627.17800603608401.4712779562288430.21536847608171.722728078
2287993.83748029607752.738407883
#Sta/Elev= 30
       0 3711.59      32 3703.45   116.3 3678.07     164 3661.34   195.3 3652.28
   211.1 3645.72   226.4 3645.44   237.8  3641.6   295.4 3631.16   329.4 3628.03
   345.5 3622.54   369.8 3617.84   394.2 3622.23   427.4 3620.21   456.5 3622.16
   461.5 3621.72   471.8 3617.96   484.1 3616.36   492.6 3614.98   499.5 3615.13
   502.7 3616.38   510.6 3618.97   589.3 3614.32   597.3 3615.79   602.9 3618.31
   623.9 3632.54   665.9  3640.8   718.9 3654.38   775.5 3682.44   907.6 3729.47
#Mann= 8 ,-1,0
       0      .1       0      30     .06       0     290     .12       0
  432.62      .1       0  442.62     .12       0   484.1    .045       0
   502.7     .12       0  712.62      .1       0
#XS Ineff= 2 , 0
                          546.57         3628.48
Permanent Ineff=
       F       F
Bank Sta=484.1,502.7
XS Rating Curve= 0 ,0
Exp/Cntr=0.3,0.1

Type RM Length L Ch R = 1 ,5763    ,271,264.6,260.9
BEGIN DESCRIPTION:
Disconnected without IFA
END DESCRIPTION:
XS GIS Cut Line= 4
 2288859.6524938608170.5786858752288656.49771377607969.978414482
2288412.58313975607756.5458489472288227.41744078607580.716235635
#Sta/Elev= 30
       0 3704.66    21.8 3698.09    41.8 3689.53    55.5 3686.39   117.3 3662.99
   184.2 3642.12   195.6 3636.69   212.6 3636.69     224 3632.13   243.9 3628.82
   306.1 3619.07   333.8  3617.4   340.2 3615.27     355 3606.39   365.7 3605.44
   376.3 3606.33   461.3 3606.87     472 3607.73   482.6 3612.94   490.4 3615.12
   523.6 3617.36   544.3 3615.17   596.5  3621.6   637.7 3631.53   707.4 3644.85
   728.3 3650.51   775.7  3668.5   819.8 3688.67   835.8 3692.51     865 3702.37
#Mann= 10 ,-1,0
       0      .1       0     130     .06       0     270     .12       0
   325.5      .1       0     355    .045       0   376.3      .1       0
   415.5     .12       0   585.5      .1       0  709.61     .12       0
  719.61      .1       0
#XS Ineff= 2 , 0
                          446.95         3613.25
Permanent Ineff=
       F       F
Bank Sta=355,376.3
XS Rating Curve= 0 ,0
Exp/Cntr(USF)=0,0
Exp/Cntr=0.3,0.1

Type RM Length L Ch R = 1 ,5498    ,444.4,454.9,461.9
XS GIS Cut Line= 4
2289014.43597575608098.9852219792288754.04194435607695.586429023
2288495.75351677607642.1429138522288299.63374325607487.675046602
#Sta/Elev= 30
       0 3710.07   127.4 3668.98   144.7 3661.14   154.5 3659.16   183.1 3645.56
   225.4 3628.93   243.1 3628.04   278.3 3618.82   321.1  3612.1   365.6 3609.27
   395.1 3604.33   445.6 3604.83   473.5 3597.23   506.6 3600.11   531.1  3599.5
   595.4 3602.89   604.6 3602.37  614.63 3597.85     625 3596.19     634  3597.9
   649.5 3599.43   682.2 3598.76   706.7  3607.9     723 3618.07   739.4 3624.49
   804.5 3643.79   868.3 3676.38   895.2 3685.73   912.3 3689.26   993.5 3717.59
#Mann= 6 ,-1,0
       0      .1       0     140     .06       0     260     .12       0
  614.63    .045       0     634     .12       0   833.9      .1       0
#XS Ineff= 2 , 0
             507 3605.94
Permanent Ineff=
       F       F
Bank Sta=614.63,634
XS Rating Curve= 0 ,0
Exp/Cntr=0.3,0.1

Type RM Length L Ch R = 1 ,5043    ,289.3,291.7,292.3
XS GIS Cut Line= 4
2289211.13676266608020.6036752692289142.13415848607740.961542518
2288887.91403779607370.5265095252288521.11072081607328.761775412
#Sta/Elev= 30
       0 3705.93    85.9 3687.68   127.5 3672.24   210.2 3647.09   267.2 3626.62
   292.2 3621.06   302.3 3615.89   321.7 3615.51   387.1 3603.79   461.9 3595.49
   530.3 3592.73   569.1 3593.14   609.6 3584.13   651.8 3587.61   661.3 3586.99
  667.773584.206   677.7 3583.01  684.793584.192   690.4 3586.38   717.9 3590.21
   734.1 3597.07   757.2  3597.3   789.4 3602.42   865.9 3622.53   922.2 3632.27
     966 3653.39   986.6 3668.89   998.7 3676.03    1039 3691.21  1106.5 3706.34
#Mann= 7 ,-1,0
       0      .1       0     140     .06       0  328.03      .1       0
  358.03     .12       0  667.77    .045       0  684.79     .12       0
  997.31      .1       0
#XS Ineff= 2 , 0
          641.16    3594
Permanent Ineff=
       F       F
Bank Sta=667.77,684.79
XS Rating Curve= 0 ,0
Exp/Cntr(USF)=0,0
Exp/Cntr=0.3,0.1

Type RM Length L Ch R = 1 ,4752    ,292.6,297.6,302.7
XS GIS Cut Line= 4
2289329.16753298607918.9156269962289256.53321278607543.033019987
2289058.60469025 607078.173370742289089.47427634 606869.34970018
#Sta/Elev= 30
       0 3687.07    77.4 3673.16   107.7 3665.64   168.8 3644.79   221.8 3623.52
   275.5 3611.45   286.9 3606.66   307.3 3606.34   402.2 3590.38   421.1 3589.51
   433.3 3593.05     476 3592.63   509.5 3577.29   558.8 3576.32   615.3 3579.67
   654.4 3579.11   665.8  3575.8   677.2 3575.43   683.3 3575.76   719.6 3581.91
   761.5 3581.34   802.3 3586.47   841.3 3586.74   863.6 3591.84   897.2 3594.81
   930.1 3606.08   994.2 3614.51  1050.8 3632.69  1075.1 3644.15  1099.2 3652.81
#Mann= 8 ,-1,0
       0      .1       0     140     .06       0     240      .1       0
  442.84     .12       0  472.84      .1       0  552.84     .12       0
   665.8    .045       0   683.3     .12       0
#XS Ineff= 2 , 0
          617.76 3587.76
Permanent Ineff=
       F       F
Bank Sta=665.8,683.3
XS Rating Curve= 0 ,0
Exp/Cntr(USF)=0,0
Exp/Cntr=0.3,0.1

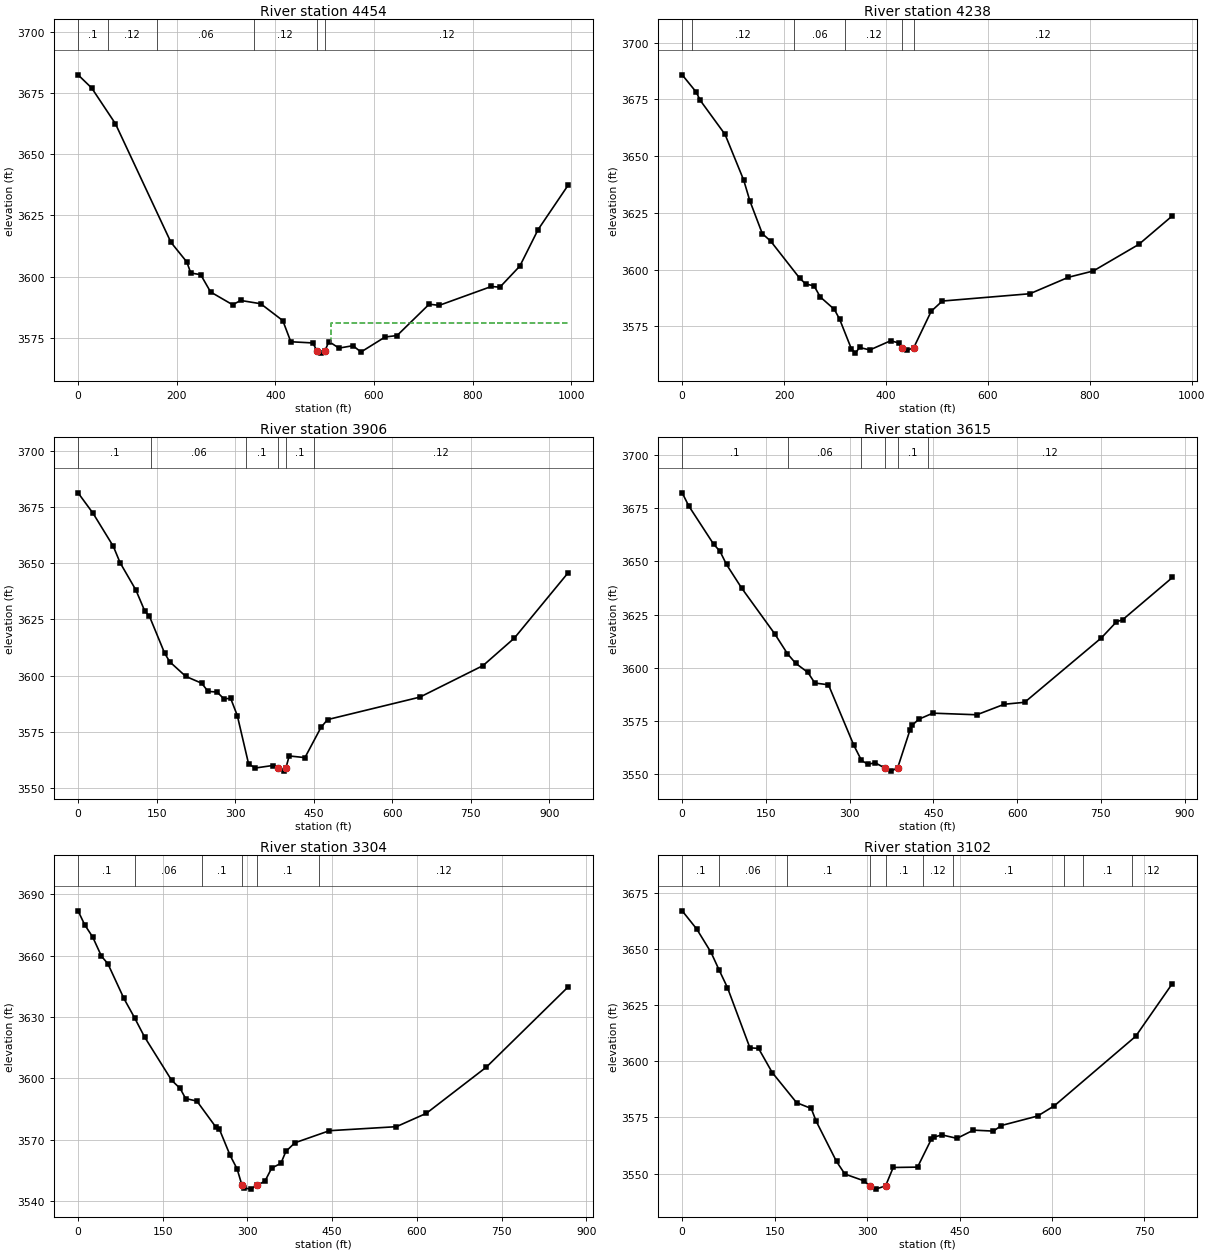
Type RM Length L Ch R = 1 ,4454    ,215.7,216,216.2
XS GIS Cut Line= 4
2289388.96408945607840.6486277892289363.66883507607575.718464075
2289463.54102534607023.697630594 2289424.3235863606861.694141218
#Sta/Elev= 30
       0 3682.34    27.6 3676.98    75.8 3662.39   188.3 3614.04   220.5 3606.02
   228.5 3601.52   248.6 3600.85   268.7 3593.79   313.4 3588.57   329.7 3590.33
   370.3 3588.99   415.1 3582.11   431.3 3573.49     476    3573   484.2 3569.82
   492.3 3568.85  500.743569.891   508.5 3573.58   528.9  3570.9   557.3 3571.88
   573.6 3569.31   622.4 3575.42   646.8 3576.03   711.8  3588.8   732.1 3588.33
   837.9 3596.03   855.2 3595.74   895.6 3604.34   932.6 3619.22   993.8 3637.42
#Mann= 6 ,-1,0
       0      .1       0      60     .12       0     160     .06       0
  356.14     .12       0   484.2    .045       0  500.74     .12       0
#XS Ineff= 2 , 0
                          511.91            3581
Permanent Ineff=
       F       F
Bank Sta=484.2,500.74
XS Rating Curve= 0 ,0
Exp/Cntr(USF)=0,0
Exp/Cntr=0.3,0.1

Type RM Length L Ch R = 1 ,4238    ,326.2,332,332.9
XS GIS Cut Line= 2
2289541.62291955607808.1482886992289706.86599799606860.270410155
#Sta/Elev= 30
       0 3685.83    27.4 3678.27    35.5 3674.57    84.2 3659.57   120.8 3639.42
   132.9 3630.28   157.3 3615.86   173.5 3612.64   230.4 3596.32   242.6 3593.66
   258.8 3592.91     271    3588   298.7 3582.51     309 3578.21   331.9 3565.25
     340 3563.25   348.1 3565.74   368.4 3564.66     409 3568.68   425.3 3567.75
   431.93565.542   441.5 3564.51  454.393565.594   488.8 3581.69   510.6 3586.19
   682.5 3589.41   758.2 3596.67     807 3599.44   896.3 3611.15   962.2 3623.74
#Mann= 6 ,-1,0
       0      .1       0      20     .12       0     220     .06       0
     320     .12       0   431.9    .045       0  454.39     .12       0
Bank Sta=431.9,454.39
XS Rating Curve= 0 ,0
Exp/Cntr(USF)=0,0
Exp/Cntr=0.3,0.1

Type RM Length L Ch R = 1 ,3906    ,290.2,290.9,293.5
XS GIS Cut Line= 2
2289695.97084996607811.7800047082290042.79972889606941.984020375
#Sta/Elev= 30
       0 3681.31    28.6 3672.22    67.4 3657.48    80.3 3650.21   110.5 3638.03
   127.7 3628.56   136.3 3626.41   165.3 3609.99   175.1 3606.12   205.7 3599.62
   236.1 3596.58   248.3 3592.94   265.5 3592.64   278.4 3589.68   291.6 3589.78
   304.2 3582.17   325.8 3560.61   338.7 3558.84   371.6 3559.95   381.8 3558.84
   393.1 3557.45  397.053558.913   403.3  3564.2   433.4 3563.47     464 3576.89
   476.5 3580.38     653 3590.39   773.6 3604.42   833.4 3616.65   936.4 3645.81
#Mann= 6 ,-1,0
       0      .1       0     140     .06       0     320      .1       0
   381.8    .045       0  397.05      .1       0     450     .12       0
Bank Sta=381.8,397.05
XS Rating Curve= 0 ,0
Exp/Cntr(USF)=0,0
Exp/Cntr=0.3,0.1

Type RM Length L Ch R = 1 ,3615    ,316.7,311.3,308
XS GIS Cut Line= 2
2289917.45972657607870.393422332 2290341.3041126607101.423249017
#Sta/Elev= 30
       0 3682.16    11.7 3676.04    56.2 3658.09    67.7 3654.72    79.4 3648.51
   106.4 3637.47   165.8 3615.93   188.6 3606.58   203.1 3602.16   225.2  3597.8
   237.6 3592.84     262 3592.02   307.4 3563.62   321.1 3556.52   332.7 3554.66
   345.4 3555.42  363.243552.898   373.9 3551.47   385.93552.985   407.9  3570.7
   412.4 3573.12   423.9 3575.85     449 3578.69   527.7 3577.93   576.9 3582.88
   613.4 3583.79   750.8 3614.04   777.8 3621.57   789.1 3622.61     878  3642.4
#Mann= 6 ,-1,0
       0      .1       0     190     .06       0     320      .1       0
  363.24    .045       0   385.9      .1       0     440     .12       0
Bank Sta=363.24,385.9
XS Rating Curve= 0 ,0
Exp/Cntr(USF)=0,0
Exp/Cntr=0.3,0.1

Type RM Length L Ch R = 1 ,3304    ,198.2,201.7,205.6
XS GIS Cut Line= 4
2290180.80493726607962.4962191132290338.78458369607748.224974538
 2290418.6823359607366.8947935152290522.18624218607181.677277018
#Sta/Elev= 30
       0 3681.98    11.9 3675.09    25.9 3669.19    41.4 3659.82    52.9 3656.06
    81.2 3639.12     100 3629.72   117.8 3620.29   165.6 3599.16   180.7 3595.15
   190.5 3590.19   210.4 3588.95   243.6 3576.39   250.1 3575.29   269.3 3562.37
   281.6  3555.8   290.2 3547.82   293.8 3546.44   306.1  3545.9  316.893547.869
   330.8 3549.74   342.9 3556.19   359.2 3558.52   367.9  3564.3   383.8 3568.54
   445.1 3574.47   563.6 3576.43   616.7 3582.96   722.9 3605.54     868 3644.84
#Mann= 6 ,-1,0
       0      .1       0     100     .06       0     220      .1       0
   290.2    .045       0  316.89      .1       0  426.21     .12       0
Bank Sta=290.2,316.89
XS Rating Curve= 0 ,0
Exp/Cntr(USF)=0,0
Exp/Cntr=0.3,0.1

Type RM Length L Ch R = 1 ,3102    ,257.9,258.2,258.3
XS GIS Cut Line= 2
2290393.84197299608034.1005374322290768.25627647607332.317110296
#Sta/Elev= 30
       0 3666.99    23.7 3658.84    46.8 3648.49      60  3640.6    73.4 3632.84
   109.9 3605.98   123.9 3605.73   146.1 3594.97   185.7 3581.54   209.4 3578.97
   217.4  3573.3   250.4 3555.37     264 3549.76   295.7 3546.68     304 3544.45
   313.9 3543.05  330.023544.489   342.4 3552.69   381.9 3552.85   404.3 3565.31
   409.1 3566.23   421.3 3567.21   445.9 3565.66   472.5 3569.32     505 3568.89
   517.9 3571.38   576.8 3575.61     604  3580.2   735.8  3611.1   795.4 3634.62
#Mann= 10 ,-1,0
       0      .1       0      60     .06       0     170      .1       0
     304    .045       0  330.02      .1       0     390     .12       0
     440      .1       0     620     .12       0     650      .1       0
     730     .12       0
Bank Sta=304,330.02
XS Rating Curve= 0 ,0
Exp/Cntr(USF)=0,0
Exp/Cntr=0.3,0.1

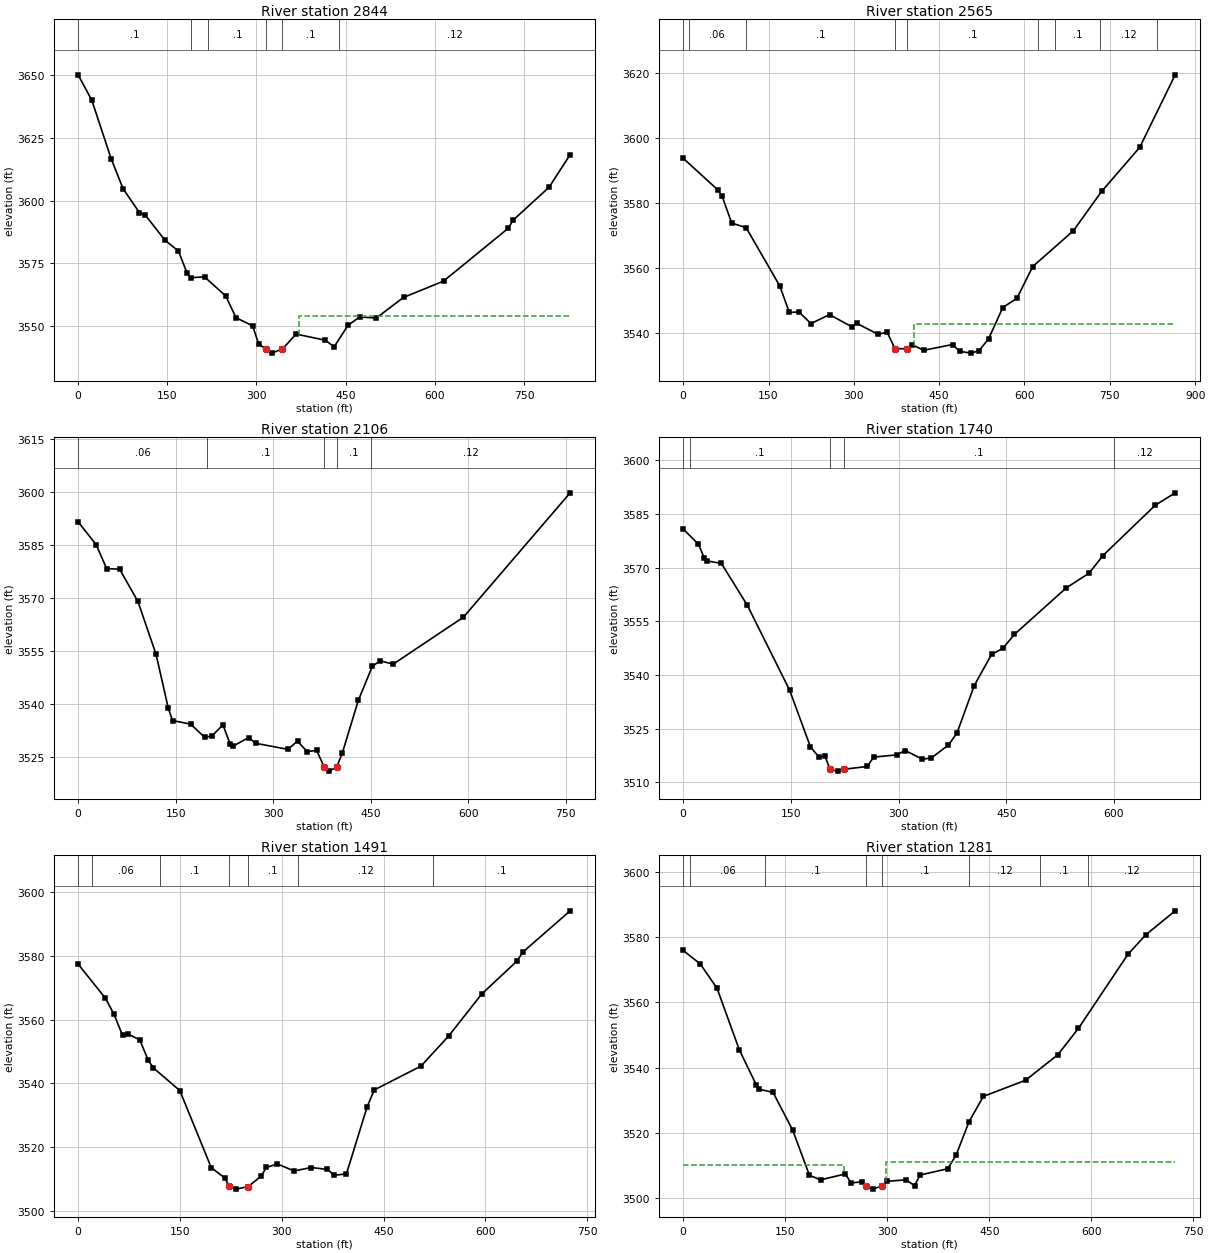
Type RM Length L Ch R = 1 ,2844    ,286.8,279,266.9
XS GIS Cut Line= 4
2290551.84821518 608121.207359732290694.69275264608013.340243249
  2290827.250387607773.6469866062290873.83338214 607401.86620592
#Sta/Elev= 30
       0 3650.14    23.1 3639.94    55.5 3616.69    75.6  3604.7   103.1 3595.17
   112.9 3594.21   145.8 3584.25   168.7 3579.84   183.1 3571.14     189 3569.21
   212.6 3569.54   248.2 3561.92   265.6 3553.25   293.5 3550.02   303.8 3542.68
   316.3 3540.77   325.5 3539.13   343.7  3540.8   366.6 3546.72   415.7 3544.28
   430.6 3541.65   454.1 3550.27   473.5 3553.53   501.7 3553.18   547.3 3561.34
   614.6 3567.86   723.5 3588.93   731.5 3592.14     792 3605.27   827.6  3618.3
#Mann= 6 ,-1,0
       0      .1       0     189     .06       0     219      .1       0
   316.3    .045       0   343.7      .1       0     439     .12       0
#XS Ineff= 2 , 0
                          371.12         3553.79
Permanent Ineff=
       F       F
Bank Sta=316.3,343.7
XS Rating Curve= 0 ,0
Exp/Cntr(USF)=0,0
Exp/Cntr=0.3,0.1

Type RM Length L Ch R = 1 ,2565    ,449.9,459.1,468.1
XS GIS Cut Line= 3
2291145.02553785 608282.087227972290968.88731138607757.304264562
2291046.96920559607455.871835754
#Sta/Elev= 30
       0 3593.71    61.4 3583.92    68.5 3582.02    85.3 3573.83   110.7  3572.4
   169.7 3554.56   186.6 3546.39   203.5 3546.55   224.6 3542.99   257.3 3545.73
   296.3 3542.01   304.7 3543.09   342.7 3539.68   358.4 3540.36   372.3 3535.27
   393.8 3535.27   401.8 3536.52   422.9 3534.79   473.5 3536.55   486.2 3534.47
   505.5 3533.91   519.9 3534.61   536.8 3538.28   561.9 3547.91   586.7 3550.74
   614.5 3560.48   685.9 3571.46   735.5 3583.51   802.5 3597.05   864.9 3619.31
#Mann= 9 ,-1,0
       0      .1       0      10     .06       0     110      .1       0
   372.3    .045       0   393.8      .1       0  623.55     .12       0
  653.55      .1       0  733.55     .12       0  833.55      .1       0
#XS Ineff= 2 , 0
                           406.5         3542.93
Permanent Ineff=
       F       F
Bank Sta=372.3,393.8
XS Rating Curve= 0 ,0
Exp/Cntr(USF)=0,0
Exp/Cntr=0.3,0.1

Type RM Length L Ch R = 1 ,2106    ,369.8,366.3,357.3
XS GIS Cut Line= 4
 2291250.8315253608272.9037906492291255.79287615608135.002729576
2291431.93110262607889.8618989182291429.22337734607573.247924842
#Sta/Elev= 30
       0 3591.59    27.7 3585.14    43.8 3578.38    63.8 3578.19    91.8 3569.12
   119.8 3554.12   138.6 3538.86   145.2 3535.37   172.9 3534.37   194.4 3530.66
   205.5 3530.97   222.7 3534.15   233.8 3528.66   238.7 3528.18     262 3530.55
   273.2 3528.93   322.5 3527.22   337.3 3529.55     352  3526.6   366.8  3526.9
   378.6  3522.1   385.4 3521.06  397.263522.125     406 3526.06   430.8 3541.08
   452.5 3550.79   464.5 3552.25   484.5 3551.34   592.5 3564.64   756.5 3599.81
#Mann= 5 ,-1,0
       0     .06       0  197.99      .1       0   378.6    .045       0
  397.26      .1       0  449.85     .12       0
Bank Sta=378.6,397.26
XS Rating Curve= 0 ,0
Exp/Cntr(USF)=0,0
Exp/Cntr=0.3,0.1

Type RM Length L Ch R = 1 ,1740    ,250.2,248.7,245.7
XS GIS Cut Line= 2
2291717.60128813608282.4844655672291705.65826376607597.355463799
#Sta/Elev= 30
       0 3580.76    21.3 3576.56    29.3 3572.67    33.3 3571.88    53.3 3571.16
    89.5 3559.42   148.2 3535.78   177.3 3519.87   189.3 3517.04   197.3 3517.41
  204.583513.599     215 3513.14   223.8 3513.66   256.4 3514.44   265.3 3517.06
   297.4 3517.68   309.3  3518.9     333 3516.49   345.4 3516.79   369.4 3520.42
   381.4 3523.83   405.4 3537.06   429.4 3545.73   445.4 3547.47   461.4 3551.36
   533.5 3564.34   565.4 3568.47   584.6 3573.37   657.4 3587.42   685.2  3590.9
#Mann= 5 ,-1,0
       0     .06       0      10      .1       0  204.58    .045       0
   223.8      .1       0     600     .12       0
Bank Sta=204.58,223.8
XS Rating Curve= 0 ,0
Exp/Cntr(USF)=0,0
Exp/Cntr=0.3,0.1

Type RM Length L Ch R = 1 ,1491    ,210.4,210.2,210.1
XS GIS Cut Line= 3
2291905.87004189608291.1665179952291967.60921406608107.764859503
2291873.18459781607584.797754099
#Sta/Elev= 30
       0 3577.41    40.1 3566.74    52.7 3561.77    65.4 3555.05    73.8 3555.45
    90.7 3553.67   103.4 3547.22   110.7 3544.89   149.8 3537.76   196.1 3513.59
   215.9 3510.38   222.8 3507.71   232.7 3506.85   250.3 3507.63   269.3 3510.84
   277.4 3513.66   293.7 3514.74   318.1 3512.53   343.3 3513.63   366.9 3513.04
   377.7 3511.21   395.3 3511.62   425.9 3532.74   436.3 3537.96     505 3545.41
   545.7 3554.81   594.6 3568.03   646.3 3578.31   655.5 3581.23   724.9 3594.12
#Mann= 7 ,-1,0
       0      .1       0      20     .06       0     120      .1       0
   222.8    .045       0   250.3      .1       0  323.51     .12       0
  523.51      .1       0
Bank Sta=222.8,250.3
XS Rating Curve= 0 ,0
Exp/Cntr(USF)=0,0
Exp/Cntr=0.3,0.1

Type RM Length L Ch R = 1 ,1281    ,262.6,261.5,255.9
XS GIS Cut Line= 4
2292138.29986652 608289.350659992292181.88045863608115.028291522
2292138.29986652607873.5191768742292025.71667021607597.508760134
#Sta/Elev= 30
       0 3575.86    24.9 3571.78    49.7 3564.33    82.6 3545.42   107.2 3534.85
   111.5  3533.4   132.1 3532.45     161 3520.86   185.6 3507.09   201.9 3505.67
   238.5  3507.5   246.6 3504.73   262.9 3505.08   268.8 3503.75   279.1 3502.84
  291.733503.787   299.4 3505.22   327.4 3505.69   340.1 3503.91   348.2 3507.16
   388.9 3509.08   401.1 3513.22   420.3 3523.52   441.3 3531.22   503.2 3536.14
   550.7 3543.96     581 3552.03     654 3574.76   680.3 3580.71   723.2 3587.99
#Mann= 8 ,-1,0
       0      .1       0      10     .06       0     120      .1       0
   268.8    .045       0  291.73      .1       0  419.69     .12       0
   525.1      .1       0   595.1     .12       0
#XS Ineff= 2 , 0
          236.85 3510.22  298.44         3511.14
Permanent Ineff=
       F       F
Bank Sta=268.8,291.73
XS Rating Curve= 0 ,0
Exp/Cntr(USF)=0,0
Exp/Cntr=0.3,0.1

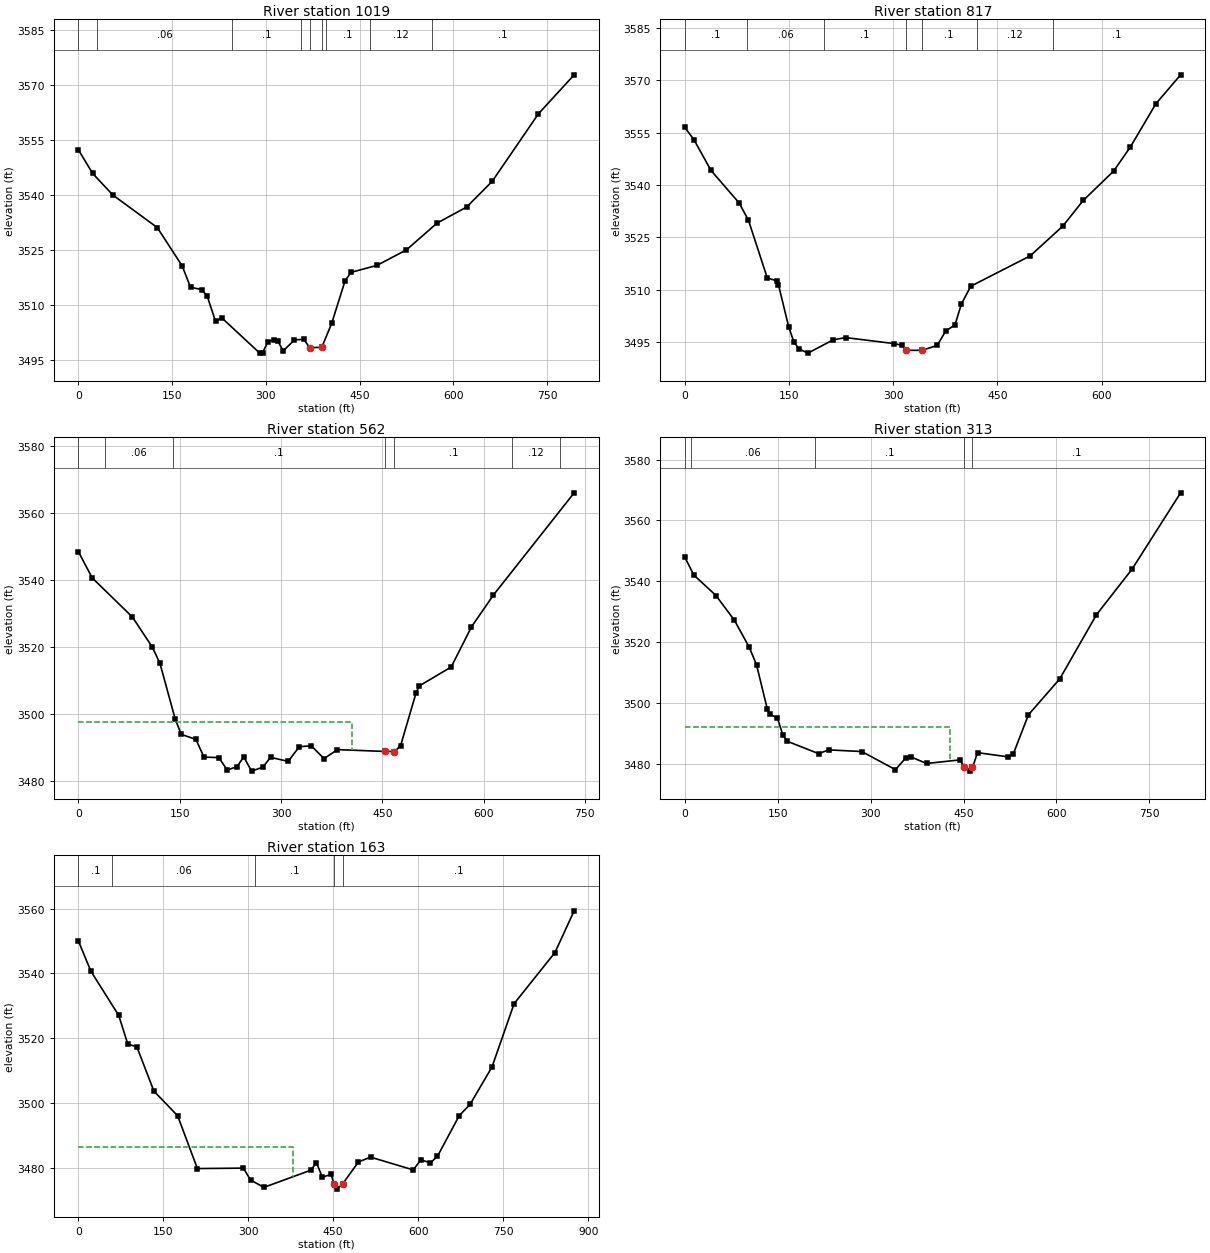
Type RM Length L Ch R = 1 ,1019    ,203,202.7,202.3
XS GIS Cut Line= 3
2292343.43038239608298.9492093642292441.54815333608095.053853468
2292198.46014744607582.706578008
#Sta/Elev= 30
       0  3552.3    22.9 3545.82    55.2 3539.94   126.3 3531.05   166.2 3520.58
   179.5 3514.77   197.3 3514.14   206.2 3512.37   219.5 3505.48   229.5 3506.43
   290.3  3496.8   294.8 3496.91   303.6 3499.96   312.5 3500.42   318.8 3500.18
   327.8  3497.4   345.8  3500.4   360.8 3500.58     370 3498.33  389.483498.353
   405.4 3504.92   426.9 3516.57   436.4 3518.84   477.9 3520.74     525 3524.96
     574 3532.27   621.4 3536.65   662.2 3543.65   736.2 3562.08   793.4 3572.72
#Mann= 9 ,-1,0
       0      .1       0      30     .06       0  246.28      .1       0
  356.28     .12       0     370    .045       0  389.48     .12       0
  396.28      .1       0  466.28     .12       0  566.28      .1       0
Bank Sta=370,389.48
XS Rating Curve= 0 ,0
Exp/Cntr(USF)=0,0
Exp/Cntr=0.3,0.1

Type RM Length L Ch R = 1 ,817     ,259.4,255,249.7
XS GIS Cut Line= 2
2292708.47928005608158.6088836392292379.80898116607524.874439939
#Sta/Elev= 30
       0 3556.49    13.2 3552.97    37.7 3544.18    78.2 3534.89    91.7  3529.9
   118.8 3513.39   132.3 3512.61   134.8  3511.5   149.6 3499.41     157 3495.13
   164.5 3493.09   177.3  3491.9   213.4 3495.68   231.4 3496.35     301 3494.64
   312.5 3494.14   318.8 3492.69  341.52 3492.71   363.3 3494.09   375.6 3498.19
   389.1 3500.02   398.1 3505.89   411.7 3511.04   497.3 3519.73   544.3 3528.25
   573.6 3535.58   617.5 3544.01   641.5 3550.88   678.3 3563.27   713.9 3571.54
#Mann= 7 ,-1,0
       0      .1       0      90     .06       0     200      .1       0
   318.8    .045       0  341.52      .1       0     420     .12       0
     530      .1       0
Bank Sta=318.8,341.52
XS Rating Curve= 0 ,0
Exp/Cntr(USF)=0,0
Exp/Cntr=0.3,0.1

Type RM Length L Ch R = 1 ,562     ,244.5,248.5,252.1
XS GIS Cut Line= 3
2292966.49521078608016.5879173022292910.03951859 607853.54473882
2292496.12958309607474.243184727
#Sta/Elev= 30
       0 3548.55    20.5 3540.68      80 3528.98   109.4 3520.02   120.8 3515.14
   143.3 3498.55   152.3  3493.9   174.1  3492.4   185.9 3487.11   208.1 3486.95
   220.4 3483.21   234.8 3484.26   244.9 3487.14   256.5 3482.91   273.2  3484.1
   284.5 3487.03   310.7 3485.82     327 3490.19   344.8 3490.49   363.8 3486.65
   383.6 3489.34   454.4 3488.79     468 3488.77     477 3490.49   499.7 3506.13
   504.6 3508.37     552 3514.04     582 3526.03   614.5 3535.55     734  3566.1
#Mann= 7 ,-1,0
       0      .1       0      40     .06       0     140      .1       0
   454.4    .045       0     468      .1       0  642.54     .12       0
  712.54      .1       0
#XS Ineff= 2 , 0
          405.49 3497.59
Permanent Ineff=
       F       F
Bank Sta=454.4,468
XS Rating Curve= 0 ,0
Exp/Cntr(USF)=0,0
Exp/Cntr=0.3,0.1

Type RM Length L Ch R = 1 ,313     ,155.1,150.6,148.3
XS GIS Cut Line= 3
2293033.51786292607989.7340891862292895.51265455607474.030415802
2292684.87312598607310.603195364
#Sta/Elev= 30
       0 3547.94    14.6 3542.07    50.3 3535.34    79.9 3527.28   104.1 3518.32
   115.9 3512.49   133.1 3498.13   137.2 3496.38   149.6 3495.03   158.3 3489.53
   164.9 3487.48   215.9 3483.39   232.5 3484.61   285.7 3484.07   340.1 3478.12
   356.7 3481.96     365 3482.31   390.3 3480.14   443.6 3481.31  451.51 3479.13
   460.2 3477.63  464.483478.829   472.6  3483.7   522.3 3482.31   530.6  3483.4
   554.8 3496.14   605.3 3507.93   664.6 3529.02   722.1 3544.01   800.5 3569.09
#Mann= 5 ,-1,0
       0      .1       0      10     .06       0     210      .1       0
  451.51    .045       0  464.48      .1       0
#XS Ineff= 2 , 0
          428.88 3492.28
Permanent Ineff=
       F       F
Bank Sta=451.51,464.48
XS Rating Curve= 0 ,0
Exp/Cntr(USF)=0,0
Exp/Cntr=0.3,0.1

Type RM Length L Ch R = 1 ,163     ,,,
XS GIS Cut Line= 4
2293225.08322049607944.4324287282293226.63248171 607742.81378576
2292959.18667221607414.4418923182292752.25577487607273.929759479
#Sta/Elev= 30
       0 3550.09    22.2 3540.69    71.3 3527.05    87.3 3518.19   103.3 3517.35
   133.3 3503.69   175.3 3496.05   210.2 3479.74   291.4 3479.88     304 3476.21
   327.5 3473.93   410.1 3479.21   420.4 3481.53   430.7 3477.08   446.2 3477.94
   451.4 3475.05   456.5 3473.39  466.523474.988   494.5 3481.78   515.9 3483.27
   591.2 3479.33   604.6 3482.43   621.6 3481.53     634 3483.53   672.3 3496.05
   691.5 3499.56   730.3 3511.13   769.3 3530.69   841.3 3546.44   875.3 3559.35
#Mann= 5 ,-1,0
       0      .1       0      60     .06       0  311.62      .1       0
   451.4    .045       0  466.52      .1       0
#XS Ineff= 2 , 0
          379.06 3486.38
Permanent Ineff=
       F       F
Bank Sta=451.4,466.52
XS Rating Curve= 0 ,0
Exp/Cntr(USF)=0,0
Exp/Cntr=0.3,0.1
LCMann Table=0

Chan Stop Cuts=-1
Use User Specified Reach Order=0
Composite Channel Slope=5